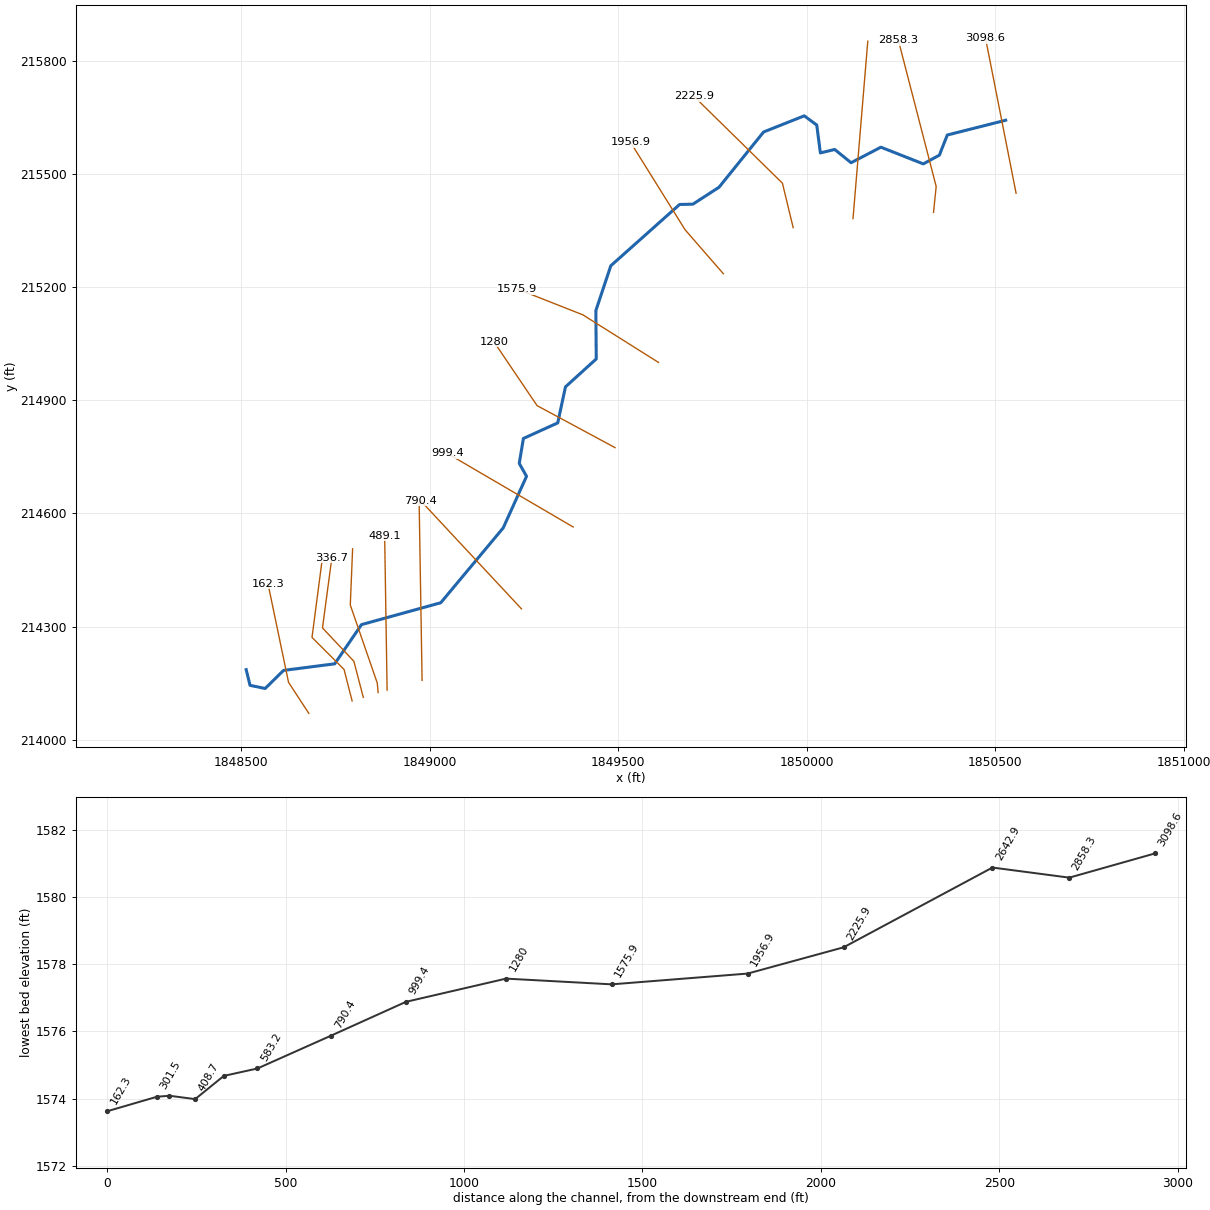
--- MUDRUN.prj (project) ---

Proj Title=MUDRUN
Current Plan=p01
Default Exp/Contr=0,0
English Units
Geom File=g01
Flow File=f01
Plan File=p01
BEGIN DESCRIPTION:
END DESCRIPTION:
DSS Export Rating Curves= 0
DSS Export Rating Curve Sorted= 0
DSS Export Volume Flow Curves= 0
DXF OffsetX= 0
DXF OffsetY= 0
DXF ScaleX= 0
DXF ScaleY= 0

--- MUDRUN.p01 (plan) ---

Plan Title=Floodplain
Program Version=4.00
Geom File=g01
Flow File=f01
K Sum by GR=0
Std Step Tol=0.01
Critical Tol=0.01
Num of Std Step Trials=20
Max Error Tol=0.3
Flow Tol Ratio=0.001
Split Flow NTrial=30
Split Flow Tol=0.02
Split Flow Ratio=0.02
Log Output Level=0
Friction Slope Method=1
Unsteady Friction Slope Method=2
Unsteady Bridges Friction Slope Method=1
Global Log Level=0
CheckData=False
Run HTab=0
Run UNet=0
Run PostProcess=0
UNET Theta=0
UNET Theta Warmup=0
UNET ZTol=0
UNET ZSATol=0
UNET MxIter=0
UNET MaxInSteps=0
UNET DtIC=0
UNET DtMin=0
UNET MaxCRTS=0
UNET WFStab=0
UNET SFStab=0
UNET WFX=0
UNET SFX=0
UNET DSS MLevel=0
UNET DZMax Abort=0
UNET Convert EG Bridges=0
UNET Use Existing IB Tables=0
UNET Froude Limit=0
UNET Froude Power=0
Write IC File=0
Echo Input=False
Echo Output=False
Write Detailed=0

--- MUDRUN.f01 (steady flow) ---

Flow Title=NFF Regression Equation
Program Version=4.10
Number of Profiles= 1
Profile Names=P100yr
River Rch & RM=MUDRUN,Main            ,3098.6
517.8515
River Rch & RM=MUDRUN,Main            ,999.4
565.1894
River Rch & RM=MUDRUN,Main            ,790.4
565.3917
Boundary for River Rch & Prof#=MUDRUN,Main            , 1
Up Type= 0
Dn Type= 3
Dn Slope=0.003
DSS Import GetInterval= 0
DSS Import GetPeak= 0
DSS Import FillOption= 0

--- MUDRUN.g01 (geometry) ---

Geom Title=USGS 10m DEM
Program Version=4.10

River Reach=MUDRUN          ,Main
Reach XY= 30
     1850527.898      215643.486     1850372.939      215604.299
     1850351.892      215550.807     1850309.328      215527.647
     1850196.758      215571.962     1850117.641      215530.742
     1850074.202      215565.968      1850036.17      215556.748
     1850026.538      215630.655     1849993.431      215655.213
     1849885.475      215612.329     1849767.175      215465.642
      1849697.83      215420.783     1849662.643      215419.999
     1849479.999      215257.309     1849440.391      215138.352
     1849441.426      215010.112     1849359.735      214935.958
      1849339.24      214840.416     1849248.128      214799.093
     1849237.114      214732.916     1849256.431      214698.675
      1849194.61      214561.818      1849028.75      214363.111
     1848818.486       214305.09     1848747.444      214201.097
     1848611.582      214183.579     1848562.971      214135.662
     1848522.693      214143.995     1848512.521      214185.653

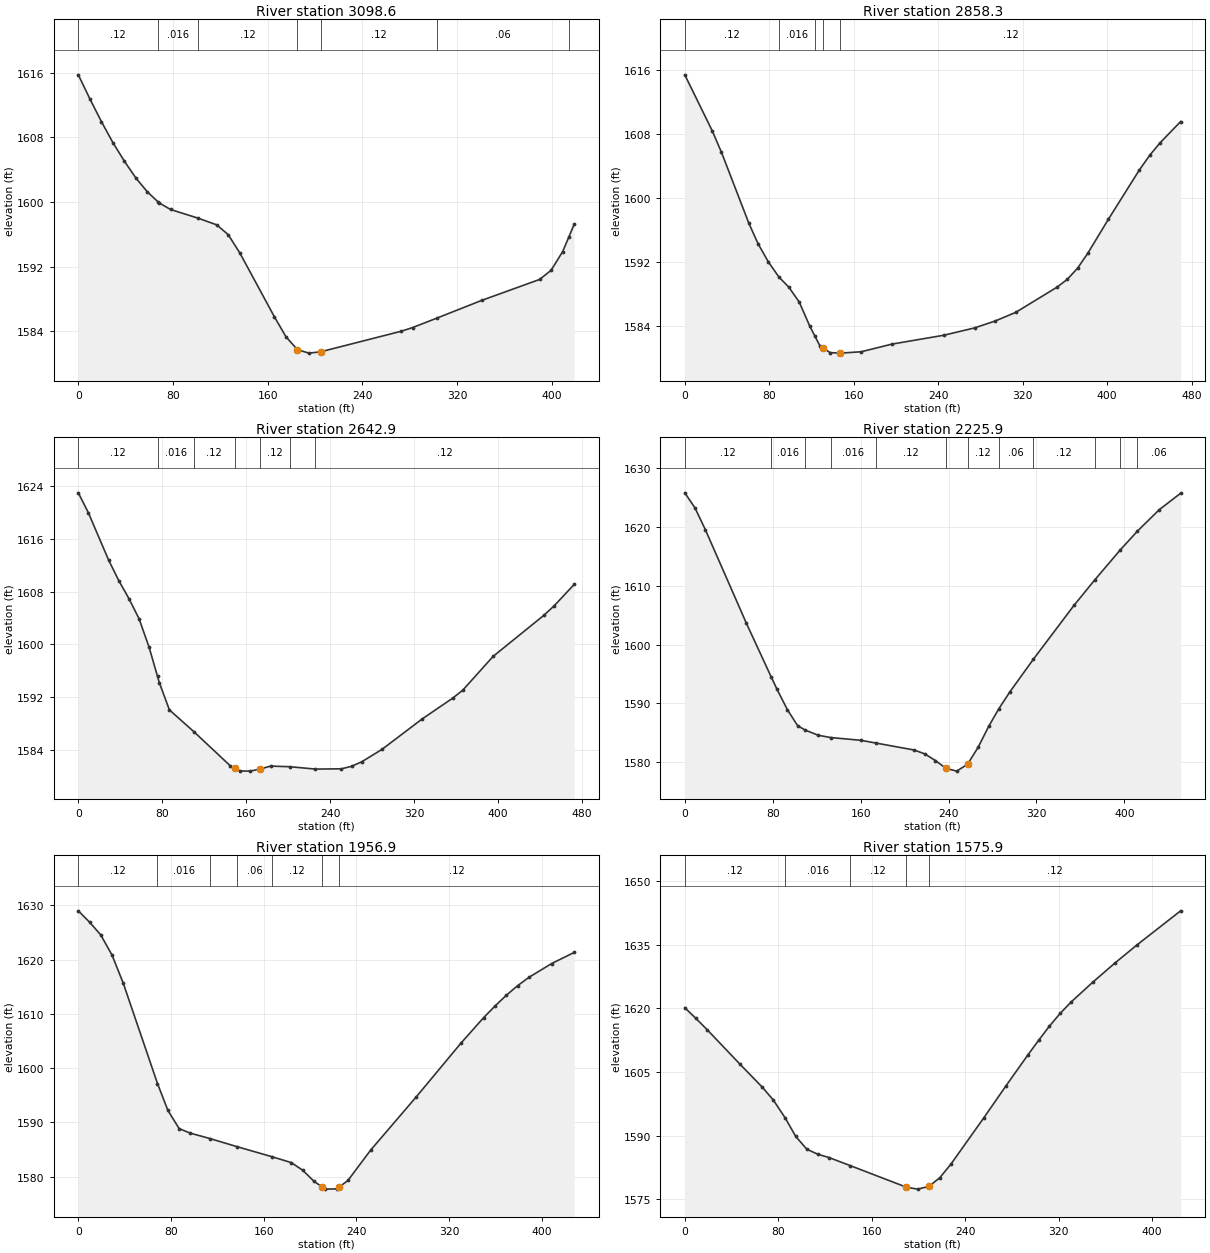
Type RM Length L Ch R = 1 ,3098.6  ,237.2,240.3,242.1
XS GIS Cut Line= 2
     1850555.466      215449.814      1850474.46       215860.83
#Sta/Elev= 28
       0 1615.74     9.7 1612.78    19.5 1609.95    29.2 1607.35      39 1605.03
    48.7 1602.95    58.4 1601.24   67.061600.056    68.2  1599.9    77.9 1599.07
  100.881598.012   116.9 1597.17   126.6 1595.96   136.4  1593.7   165.6  1585.8
   175.4 1583.32   185.1 1581.72   194.8 1581.29   204.6 1581.45   272.8    1584
   282.5 1584.46   302.61585.606     341 1587.83   389.7 1590.41   399.4 1591.54
   409.2 1593.86  414.481595.694   418.9 1597.23
#Mann= 7 ,-1 , 0
       0     .12       0   67.06    .016       0  100.88     .12       0
   185.1    .045       0   204.6     .12       0   302.6     .06       0
  414.48     .12       0
Bank Sta=185.1,204.6
XS Rating Curve= 0 ,0
Exp/Cntr=0.3,0.1

Type RM Length L Ch R = 1 ,2858.3  ,228.6,215.3,192.6
XS GIS Cut Line= 3
     1850336.376      215398.803     1850343.439      215467.806
     1850243.207      215855.271
#Sta/Elev= 30
       0 1615.34      26 1608.34    34.7 1605.67    60.7 1596.79    69.4 1594.23
    79.1 1591.98   89.171590.073    98.6  1588.8   108.4 1586.95   118.2 1583.99
  123.161582.712   127.9 1581.49   130.6 1581.25   137.7 1580.63   147.4 1580.57
     167 1580.74   196.3  1581.7   245.1  1582.8   274.4 1583.72   293.9 1584.58
   313.4 1585.66   352.4  1588.8   362.2 1589.78     372 1591.18   381.7 1593.05
   401.2  1597.3   430.5 1603.45   440.3 1605.28   450.1 1606.84   469.6  1609.5
#Mann= 5 ,-1 , 0
       0     .12       0   89.17    .016       0  123.16     .12       0
   130.6    .045       0   147.4     .12       0
Bank Sta=130.6,147.4
XS Rating Curve= 0 ,0
Exp/Cntr=0.3,0.1

Type RM Length L Ch R = 1 ,2642.9  ,380.1,417.1,434.1
XS GIS Cut Line= 2
     1850122.742       215382.37     1850161.988      215853.318
#Sta/Elev= 30
       0 1622.91     9.6 1619.89    28.9 1612.74    38.6 1609.64    48.2 1606.94
    57.9 1603.88    67.5 1599.56   75.481595.175    77.2 1594.23    86.8 1590.12
   110.11586.833   144.7 1581.69   148.9 1581.34   154.3  1580.9   163.9 1580.87
   173.6  1581.2   183.2 1581.63   201.71581.535  225.971581.179   250.8 1581.22
   260.4  1581.6     270 1582.27   289.3 1584.14   327.9 1588.77   356.8 1591.89
   366.5 1593.11   395.4 1598.21   443.6 1604.39   453.3  1605.8   472.6 1609.07
#Mann= 7 ,-1 , 0
       0     .12       0   75.48    .016       0   110.1     .12       0
   148.9    .045       0   173.6     .12       0   201.7     .06       0
  225.97     .12       0
Bank Sta=148.9,173.6
XS Rating Curve= 0 ,0
Exp/Cntr=0.3,0.1

Type RM Length L Ch R = 1 ,2225.9  ,278.3,269,259.8
XS GIS Cut Line= 3
      1849963.96      215358.502     1849935.453      215476.487
     1849700.038      215707.515
#Sta/Elev= 30
       0  1625.8     9.3 1623.23    18.7 1619.54      56 1603.65   78.82 1594.43
      84 1592.38    93.4 1588.93   102.7 1586.22  109.481585.484   121.4  1584.6
  132.711584.208   160.2 1583.74  173.961583.271   208.7 1582.09   218.4 1581.43
   228.1 1580.29   237.8 1578.96   247.5  1578.5   257.4 1579.69   266.9 1582.54
   276.6 1586.13  285.851589.124     296 1592.02  317.241597.527   354.2 1606.68
   372.91610.963  396.271616.098  411.911619.294   431.8 1622.94   451.2 1625.73
#Mann= 12 ,-1 , 0
       0     .12       0   78.82    .016       0  109.48     .12       0
  132.71    .016       0  173.96     .12       0   237.8    .045       0
   257.4     .12       0  285.85     .06       0  317.24     .12       0
   372.9     .06       0  396.27     .12       0  411.91     .06       0
Bank Sta=237.8,257.4
XS Rating Curve= 0 ,0
Exp/Cntr=0.3,0.1

Type RM Length L Ch R = 1 ,1956.9  ,364.6,381,398.4
XS GIS Cut Line= 3
     1849778.781      215236.167     1849677.207      215352.789
     1849532.641      215584.667
#Sta/Elev= 30
       0 1628.99     9.7  1626.9    19.3 1624.57      29 1620.87    38.7  1615.7
   68.321597.168    77.3 1592.22      87 1588.87    96.7 1588.03   113.91587.018
   137.11585.534  167.29 1583.68   183.9  1582.6   193.7 1581.19   203.4 1579.16
   209.9  1578.2   213.2 1577.72     223 1577.77   224.9 1578.07   232.7 1579.32
   252.2 1584.89   291.3 1594.63   330.3 1604.64   349.8 1609.32   359.6 1611.45
   369.4 1613.44   379.1  1615.2   388.9 1616.74   408.4 1619.27   427.9 1621.32
#Mann= 7 ,-1 , 0
       0     .12       0   68.32    .016       0   113.9     .12       0
   137.1     .06       0  167.29     .12       0   209.9    .045       0
   224.9     .12       0
Bank Sta=209.9,224.9
XS Rating Curve= 0 ,0
Exp/Cntr=0.3,0.1

Type RM Length L Ch R = 1 ,1575.9  ,293,295.9,291.1
XS GIS Cut Line= 3
     1849606.677      215000.768     1849405.939      215127.094
      1849231.92      215195.767
#Sta/Elev= 28
       0 1620.15     9.5 1617.63      19 1615.01    47.4 1606.79    66.4  1601.4
    75.9 1598.34   86.051594.115    94.9 1589.83   104.4 1586.81   113.8 1585.62
   123.3 1584.85  141.391582.959   189.7 1577.85   199.2  1577.4   208.8 1578.03
   218.2 1580.08   227.7 1583.28   255.9 1594.21   274.6 1601.64   293.3 1608.91
   302.7 1612.43     312  1615.8   321.4 1618.87   330.7 1621.52   349.4 1626.23
   368.1 1630.68   386.8 1634.91   424.3 1642.98
#Mann= 5 ,-1 , 0
       0     .12       0   86.05    .016       0  141.39     .12       0
   189.7    .045       0   208.8     .12       0
Bank Sta=189.7,208.8
XS Rating Curve= 0 ,0
Exp/Cntr=0.3,0.1

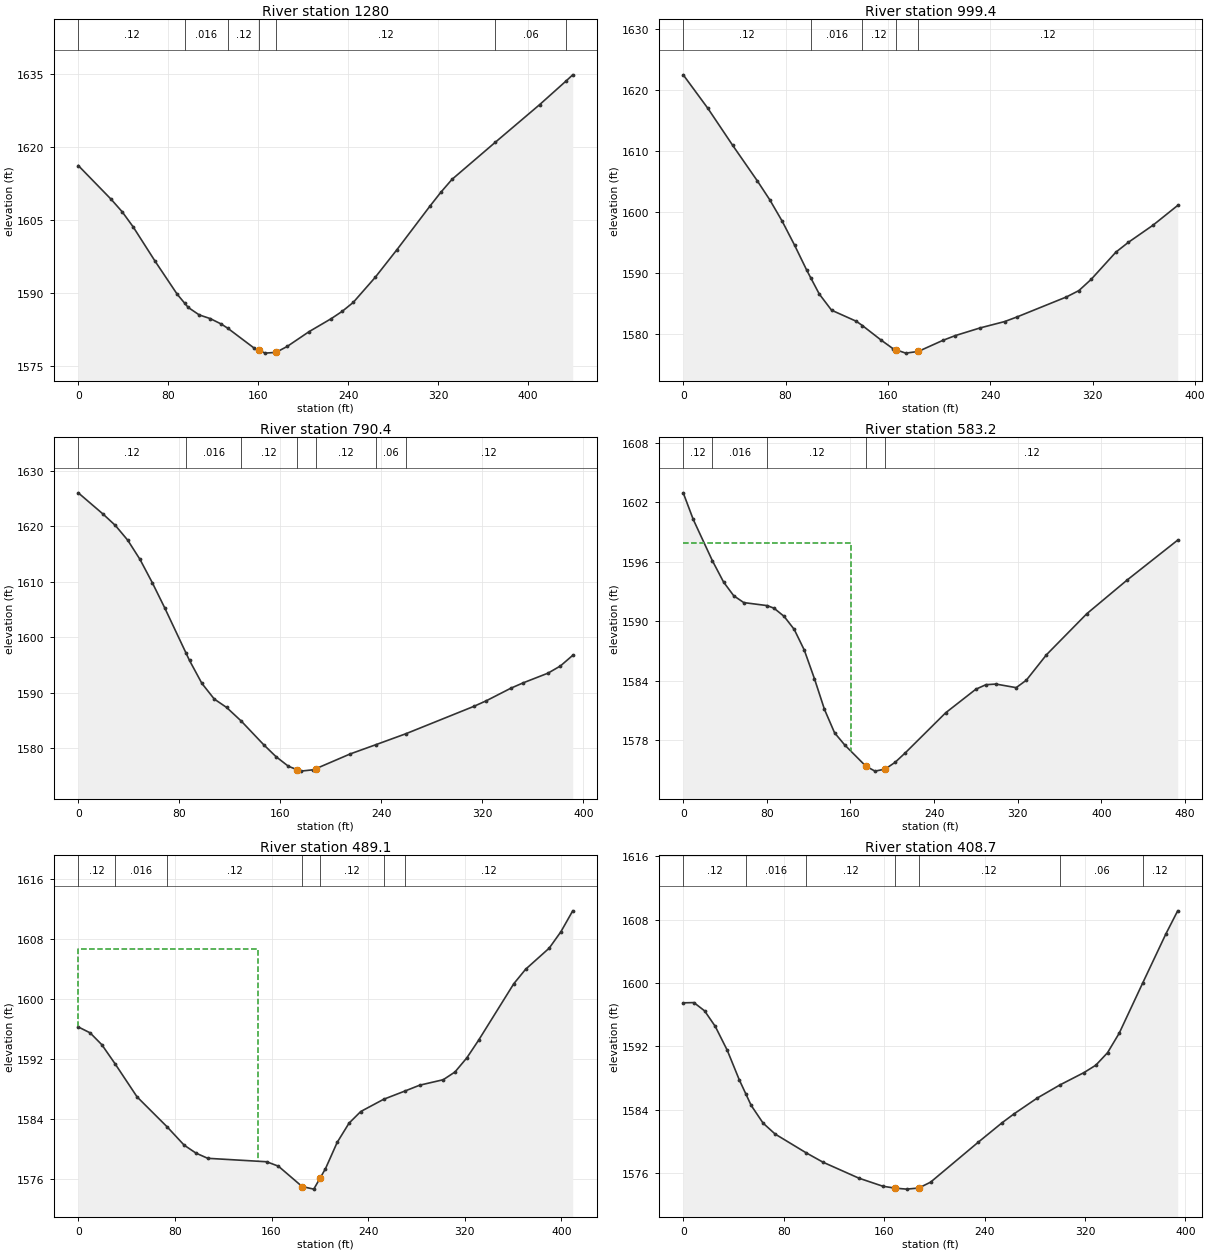
Type RM Length L Ch R = 1 ,1280    ,281.7,280.6,272.7
XS GIS Cut Line= 3
     1849491.119      214774.837     1849284.412      214886.209
     1849169.562      215056.139
#Sta/Elev= 30
       0 1616.19    29.4  1609.2    39.1 1606.66    48.9 1603.54    68.5 1596.44
      88  1589.7   94.611587.865    97.8 1586.98   107.6 1585.44   117.4 1584.68
   127.2 1583.56  133.051582.688   156.5  1578.6     161 1578.13   166.3 1577.57
     176 1577.73   185.9 1578.95   205.4    1582     225 1584.66   234.8 1586.17
   244.6    1588   264.1 1593.15   283.6 1598.89   312.9 1607.84   322.7 1610.72
   332.5 1613.34  370.891620.951   410.6 1628.75  434.02  1633.6   439.9 1634.86
#Mann= 7 ,-1 , 0
       0     .12       0   94.61    .016       0  133.05     .12       0
     161    .045       0     176     .12       0  370.89     .06       0
  434.02     .12       0
Bank Sta=161,176
XS Rating Curve= 0 ,0
Exp/Cntr=0.3,0.1

Type RM Length L Ch R = 1 ,999.4   ,220.1,209,197.8
XS GIS Cut Line= 2
     1849380.169       214564.19     1849046.564      214759.256
#Sta/Elev= 30
       0 1622.44    19.3 1616.94    38.6 1610.91      58 1605.05    67.6 1601.99
    77.3 1598.49      87 1594.56    96.6 1590.42   99.911589.103   106.3 1586.56
   115.9 1583.91   135.3 1582.09  140.071581.385   154.6 1579.02   164.2 1577.57
   165.9 1577.45   173.9 1576.88   183.6 1577.15   202.9 1578.97   212.6 1579.75
   231.9    1581   251.2 1582.05   260.8  1582.8   299.5 1586.08   309.2 1587.12
   318.8 1588.96   338.1 1593.41   347.8 1595.01   367.1 1597.82   386.4 1601.06
#Mann= 5 ,-1 , 0
       0     .12       0   99.91    .016       0  140.07     .12       0
   165.9    .045       0   183.6     .12       0
Bank Sta=165.9,183.6
XS Rating Curve= 0 ,0
Exp/Cntr=0.3,0.1

Type RM Length L Ch R = 1 ,790.4   ,234.8,207.2,178.9
XS GIS Cut Line= 2
     1849242.962      214346.929     1848976.035      214633.388
#Sta/Elev= 30
       0 1626.02    19.6  1622.2    29.4 1620.14    39.2 1617.48    48.9 1614.02
    58.7  1609.8    68.5 1605.28   85.481597.084    88.1 1595.82    97.9 1591.69
   107.7 1588.87   117.5 1587.35  129.081584.899   146.8 1580.65   156.6 1578.49
   166.4 1576.76     173 1576.17   176.2 1575.88     186 1576.12     188  1576.3
   215.4 1578.98  235.531580.631  259.421582.612   313.2 1587.54     323 1588.54
   342.6 1590.82   352.4 1591.79     372 1593.53   381.8 1594.82   391.6 1596.74
#Mann= 7 ,-1 , 0
       0     .12       0   85.48    .016       0  129.08     .12       0
     173    .045       0     188     .12       0  235.53     .06       0
  259.42     .12       0
Bank Sta=173,188
XS Rating Curve= 0 ,0
Exp/Cntr=0.5,0.3

Type RM Length L Ch R = 1 ,583.2   ,94.4,94.1,94.1
XS GIS Cut Line= 2
      1848979.29      214157.042     1848971.466      214629.969
#Sta/Elev= 30
       0 1602.97     9.6 1600.28   27.86 1596.13    38.6 1593.97    48.3 1592.59
    57.9  1591.9   80.331591.594    86.9 1591.33    96.5 1590.51   106.2 1589.19
   115.8 1587.11   125.5 1584.23   135.1 1581.13   144.8 1578.76   154.4 1577.55
   174.6 1575.41   183.4  1574.9   193.1  1575.1   202.7 1575.79   212.4 1576.74
     251 1580.78   279.9 1583.16   289.6 1583.62   299.2 1583.68   318.5 1583.32
   328.2 1584.07   347.5 1586.64   386.1 1590.78   424.7 1594.18     473  1598.2
#Mann= 5 ,-1 , 0
       0     .12       0   27.86    .016       0   80.33     .12       0
   174.6    .045       0   193.1     .12       0
#XS Ineff= 2 , 0
          160.78 1597.95
Permanent Ineff=
       F       F
Bank Sta=174.6,193.1
XS Rating Curve= 0 ,0
Exp/Cntr=0.5,0.3

Type RM Length L Ch R = 1 ,489.1   ,73.9,80.4,91.2
XS GIS Cut Line= 2
     1848886.462      214131.327     1848879.964      214540.663
#Sta/Elev= 30
       0 1596.31     9.8 1595.52    19.5 1593.94   30.391591.416    48.7 1586.98
   73.821582.946    87.7 1580.54    97.5 1579.48   107.2 1578.79     156 1578.33
   165.7 1577.74   185.4 1575.02     195 1574.68   200.4  1576.2   204.7 1577.41
   214.4 1580.92   224.2 1583.48   233.9 1585.03  252.861586.662  270.431587.757
   282.7 1588.54   302.2 1589.27   311.9  1590.3   321.7 1592.18   331.4 1594.52
   360.6 1602.07   370.4    1604   389.9 1606.81   399.6    1609   409.4 1611.79
#Mann= 7 ,-1 , 0
       0     .12       0   30.39    .016       0   73.82     .12       0
   185.4    .045       0   200.4     .12       0  252.86     .06       0
  270.43     .12       0
#XS Ineff= 2 , 0
          148.67 1606.64
Permanent Ineff=
       F       F
Bank Sta=185.4,200.4
XS Rating Curve= 0 ,0
Exp/Cntr=0.5,0.3

Type RM Length L Ch R = 1 ,408.7   ,51.1,72,89
XS GIS Cut Line= 4
     1848862.611      214124.662     1848860.367      214150.098
     1848788.752      214357.129     1848794.926      214506.249
#Sta/Elev= 30
       0  1597.5     8.5 1597.53      17 1596.49    25.5 1594.53    35.1  1591.5
    44.6  1587.8   50.021585.952    54.1 1584.56    63.6 1582.32    73.2 1580.94
   97.871578.575   111.3 1577.39   139.8 1575.38   158.9 1574.36   168.4 1574.12
   177.9 1573.99   187.6 1574.13     197 1574.87   235.1 1579.93   253.9 1582.36
   263.3 1583.47   281.9 1585.48     3001587.137   319.2  1588.7   328.6 1589.63
   337.9  1591.2   347.2 1593.66     3661600.024   384.5 1606.23   393.8 1609.11
#Mann= 7 ,-1 , 0
       0     .12       0   50.02    .016       0   97.87     .12       0
   168.4    .045       0   187.6     .12       0     300     .06       0
     366     .12       0
Bank Sta=168.4,187.6
XS Rating Curve= 0 ,0
Exp/Cntr=0.5,0.3

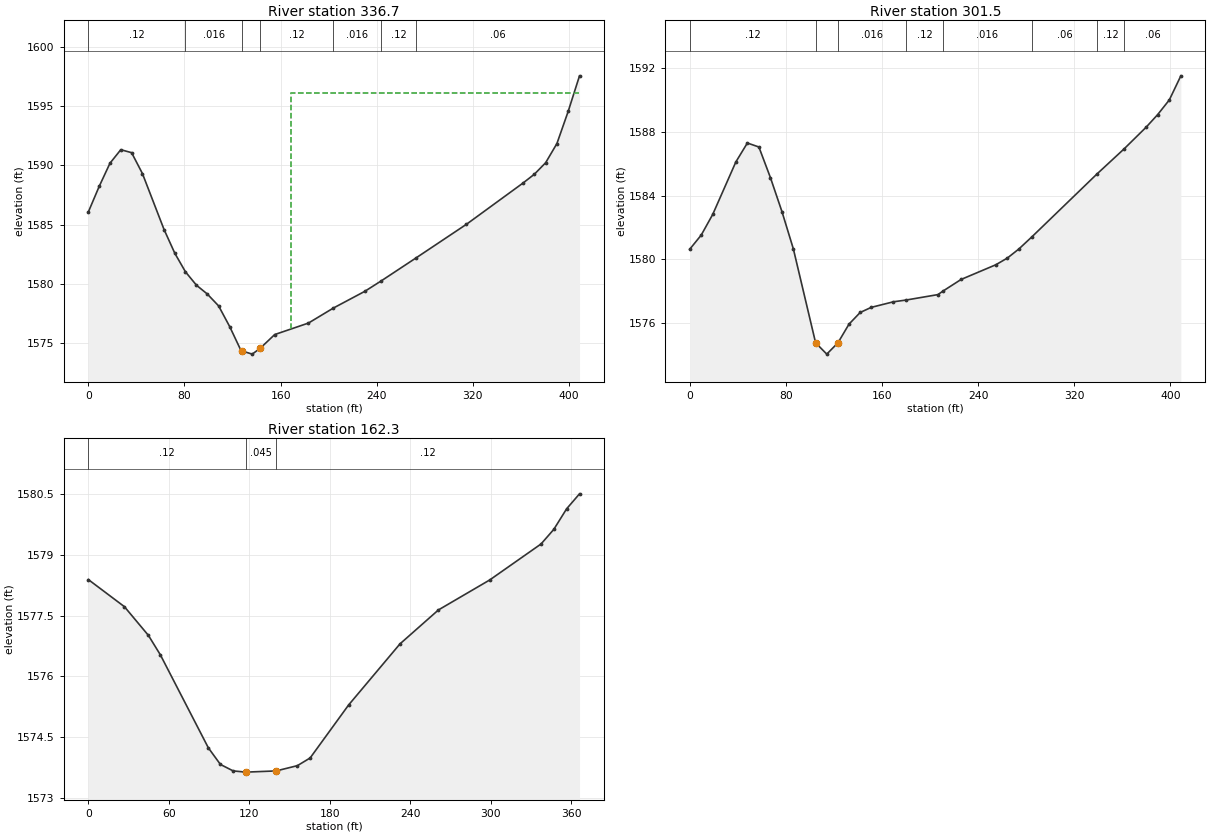
Type RM Length L Ch R = 1 ,336.7   ,38.9,35.2,36.8
XS GIS Cut Line= 4
     1848823.261         214112.     1848798.301      214207.824
     1848714.967      214296.365     1848739.904      214482.897
#Sta/Elev= 30
       0 1586.08       9 1588.23      18 1590.19      27 1591.33      36 1591.08
      45 1589.32      63  1584.6      72 1582.59   80.811581.034      90  1579.9
      99 1579.16   108.4 1578.16   117.7  1576.4   127.1 1574.38   128.1 1574.35
   136.4 1574.09   143.1 1574.59   155.1 1575.74   183.2 1576.71  203.941577.976
     230 1579.38  243.691580.261  272.531582.189   314.7 1585.04   361.8 1588.52
   371.2 1589.26   380.6 1590.23     390 1591.85   399.4 1594.57   408.8 1597.56
#Mann= 7 ,-1 , 0
       0     .12       0   80.81    .016       0   128.1    .045       0
   143.1     .12       0  203.94    .016       0  243.69     .12       0
  272.53     .06       0
#XS Ineff= 2 , 0
                          168.98         1596.14
Permanent Ineff=
       F       F
Bank Sta=128.1,143.1
XS Rating Curve= 0 ,0
Exp/Cntr=0.5,0.3

Type RM Length L Ch R = 1 ,301.5   ,153.1,139.2,114.9
XS GIS Cut Line= 4
     1848793.629      214102.465     1848772.259      214186.122
     1848687.189      214271.192     1848713.367      214471.634
#Sta/Elev= 30
       0 1580.63     9.6 1581.52    19.2 1582.82    38.4  1586.1      48 1587.29
    57.6 1587.04    67.2 1585.12    76.8 1582.99    86.3 1580.65   104.8 1574.77
   114.1 1574.06   123.4 1574.77   132.6 1575.94   141.9 1576.67   151.1 1576.99
   169.6 1577.34  180.081577.449   206.6 1577.79  210.731578.007   225.9 1578.74
   254.8 1579.66   264.4 1580.08     274 1580.65  284.971581.421  339.131585.359
  361.661586.929   379.9 1588.28   389.5 1589.07   399.2 1589.99   408.8  1591.5
#Mann= 8 ,-1 , 0
       0     .12       0   104.8    .045       0   123.4    .016       0
  180.08     .12       0  210.73    .016       0  284.97     .06       0
  339.13     .12       0  361.66     .06       0
Bank Sta=104.8,123.4
XS Rating Curve= 0 ,0
Exp/Cntr=0.5,0.3

Type RM Length L Ch R = 1 ,162.3   ,226.4,162.3,94.8
XS GIS Cut Line= 3
     1848678.726      214069.586     1848624.906      214152.051
     1848570.219      214414.204
#Sta/Elev= 19
       0 1578.39    26.9 1577.72    44.8 1577.01    53.7 1576.53    89.5 1574.23
    98.5 1573.82     108 1573.66   117.6 1573.63   140.1 1573.66   155.9 1573.79
   165.4 1573.98   194.1 1575.29   232.4  1576.8   261.1 1577.64   299.3 1578.38
   337.6 1579.27   347.1 1579.63   356.7 1580.14   366.3 1580.51
#Mann= 3 ,-1 , 0
       0     .12       0   117.6    .045       0   140.1     .12       0
Bank Sta=117.6,140.1
XS Rating Curve= 0 ,0
Exp/Cntr=0.3,0.1

Chan Stop Cuts=-1
Use User Specified Reach Order=0
Composite Channel Slope=5